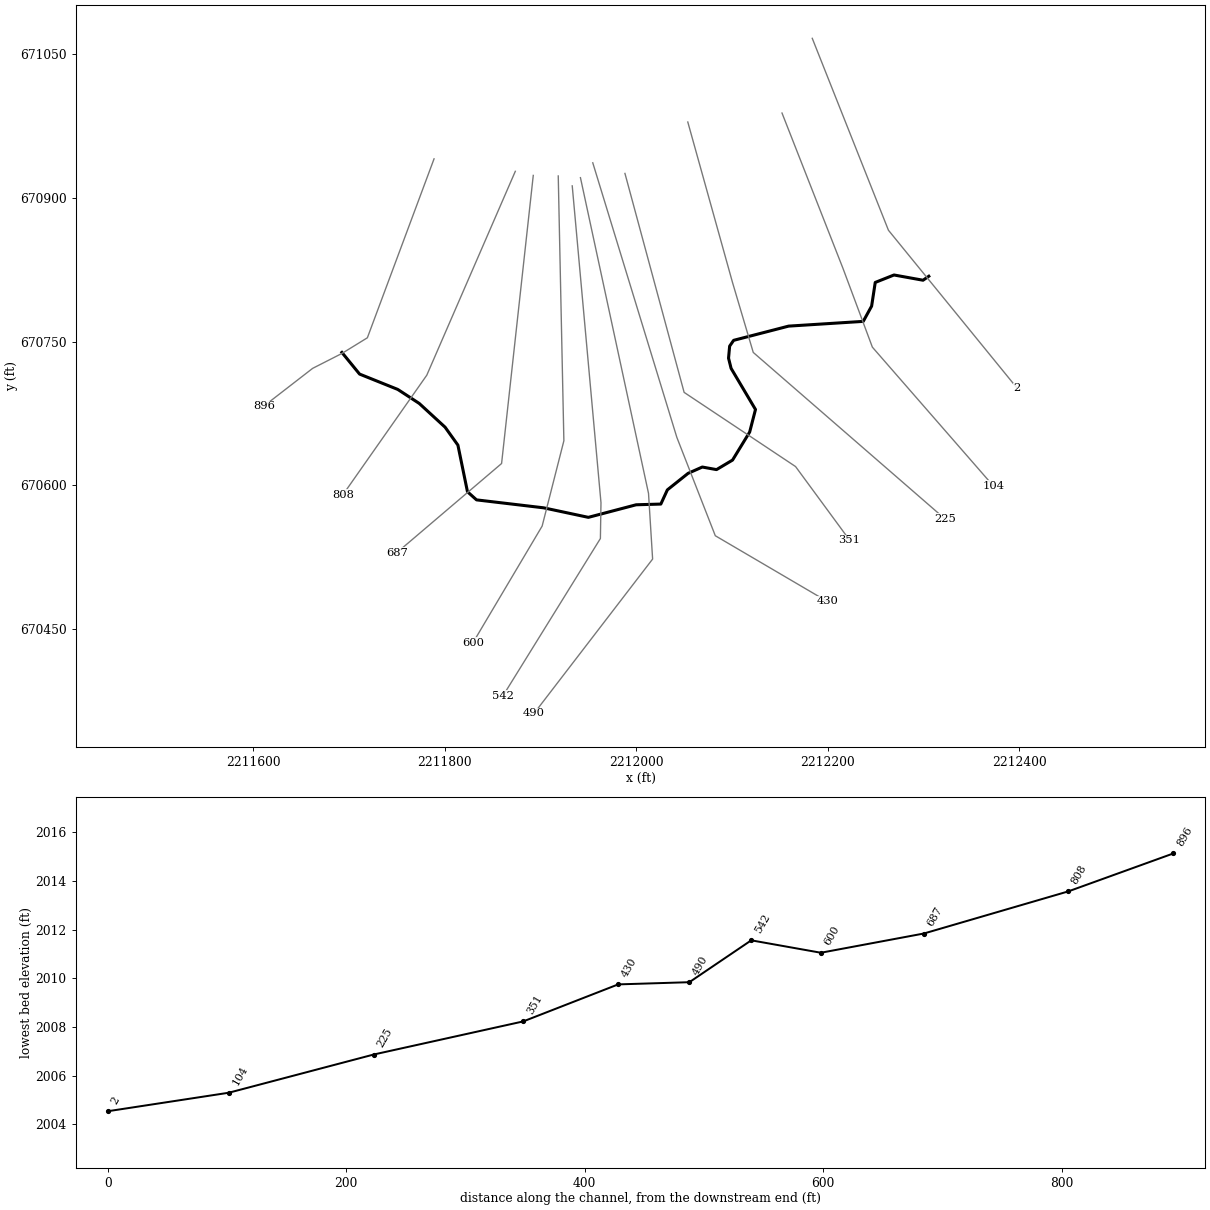
--- RFMIDFT1.prj (project) ---

Proj Title=RFMIDFT1
Current Plan=p01
Default Exp/Contr=0.3,0.1
English Units
Geom File=g01
Flow File=f01
Plan File=p01
Y Axis Title=Elevation
X Axis Title(PF)=Main Channel Distance
X Axis Title(XS)=Station
BEGIN DESCRIPTION:
---------- MODELED AS PART OF WVEMD CTP PROGRAM, 2023----------
Stream Name:Right Fork Middle Fork Tributary 1
Flood Zone:  AFH
Upshur County, WV
HEC-RAS Version: RAS 6.3
Vertical Datum: NAVD88
Projection: NAD 1983 StatePlane West Virginia S FIPS 4702 (US Feet)
Terrain: 1-meter LIDAR (FEMA Region III 3DEP collected 2016-2018)
Land Use: 2019 NLCD
Hydrologic Method:
WV SIR2010-5033 regression equations
Additional Model Notes:
None
END DESCRIPTION:
DSS Export Rating Curves= 0
DSS Export Rating Curve Sorted= 0
DSS Export Volume Flow Curves= 0
DXF OffsetX= 0
DXF OffsetY= 0
DXF ScaleX= 1
DXF ScaleY= 10

--- RFMIDFT1.p01 (plan) ---

Plan Title=Floodplain
Program Version=6.30
Short Identifier=Floodplain
Geom File=g01
Flow File=f01
Subcritical Flow
K Sum by GR= 0
Std Step Tol= 0.01
Critical Tol= 0.01
Num of Std Step Trials= 20
Max Error Tol= 0.3
Flow Tol Ratio= 0.001
Split Flow NTrial= 30
Split Flow Tol= 0.02
Split Flow Ratio= 0.02
Log Output Level= 0
Friction Slope Method= 1
Unsteady Friction Slope Method= 2
Unsteady Bridges Friction Slope Method= 1
Parabolic Critical Depth
Global Vel Dist= 0 , 0 , 0
Global Log Level= 0
CheckData=True
Encroach Param=-1 ,0,0, 0
Computation Interval=1MIN
Output Interval=1HOUR
Instantaneous Interval=1HOUR
Mapping Interval=1HOUR
Computation Time Step Use Courant=        0
Computation Time Step Use Time Series=    0
Computation Time Step Count To Double=0
Computation Time Step Max Doubling=0
Computation Time Step Max Halving=0
Computation Time Step Residence Courant=0
Run HTab= 0
Run UNet= 0
Run Sediment= 0
Run PostProcess= 0
Run WQNet= 0
Run RASMapper= 0
UNET Theta= 1
UNET Theta Warmup= 1
UNET ZTol= 0.02
UNET ZSATol= 0.02
UNET MxIter= 20
UNET Max Iter WO Improvement= 0
UNET MaxInSteps= 0
UNET DtIC= 0
UNET DtMin= 0
UNET MaxCRTS= 20
UNET WFStab= 2
UNET SFStab= 1
UNET WFX= 1
UNET SFX= 1
UNET Gravity=32.17405
UNET 1D Methodology=Finite Difference
UNET DSS MLevel= 4
UNET Pardiso=0
UNET DZMax Abort= 100
UNET Use Existing IB Tables=-1
UNET Froude Reduction=False
UNET Froude Limit= 0.8
UNET Froude Power= 4
UNET D1 Cores= 0
UNET WindReference=Eulerian
UNET WindDragFormulation=Hsu (1988)
UNET D2 Coriolis=0
UNET D2 Cores= 0
UNET D2 Theta= 1
UNET D2 Theta Warmup= 1
UNET D2 Z Tol= 0.01
UNET D2 Volume Tol= 0.01
UNET D2 Max Iterations= 20
UNET D2 Equation= 0
UNET D2 RampUpFraction=0.1
UNET D2 TimeSlices= 1
UNET D2 Turbulence Formulation=None
UNET D2 Eddy Viscosity=0.3
UNET D2 Transverse Eddy Viscosity=0.1
UNET D2 Smagorinsky Mixing=0.05
UNET D2 BCVolumeCheck=0
UNET D2 Cores=0
UNET D2 SolverType=PARDISO (Direct)
UNET D2 Minimum Iterations= 3
UNET D2 Maximum Iterations= 30
UNET D2 Restart Number= 10
UNET D2 Relaxation Coeff=1.3
UNET D2 SOR Precondition Iterations= 10
UNET D2 ILUT Maximum Fill= 8
UNET D2 ILUT Tolerance=1E-08
UNET D2 Convergence Tolerance=0.00001
UNET D1D2 MaxIter= 0
UNET D1D2 ZTol=0.01
UNET D1D2 QTol=0.1
UNET D1D2 MinQTol=1
Write IC File= 0
Write IC File at Fixed DateTime=0
Write IC File at Sim End=0
Echo Input=False
Echo Parameters=False
Echo Output=False
Write Detailed= 0
HDF Write Warmup=0
HDF Write Time Slices=0
HDF Flush=0
HDF Compression= 1
HDF Chunk Size= 1
HDF Spatial Parts= 1
HDF Use Max Rows=0
HDF Fixed Rows= 1
Calibration Method= 0
Calibration Iterations= 20
Calibration Max Change=0.05
Calibration Tolerance=0.2
Calibration Maximum=1.5
Calibration Minimum=0.5
Calibration Optimization Method= 1
WQ AD Non Conservative
WQ ULTIMATE=-1
WQ Max Comp Step=1HOUR
WQ Output Interval=15MIN
WQ Output Selected Increments= 0
WQ Output face flow=0
WQ Output face velocity=0
WQ Output face area=0
WQ Output face dispersion=0
WQ Output cell volume=0
WQ Output cell surface area=0
WQ Output cell continuity=0
WQ Output cumulative cell continuity=0
WQ Output face conc=0
WQ Output face dconc_dx=0
WQ Output face courant=0
WQ Output face peclet=0
WQ Output face adv mass=0
WQ Output face disp mass=0
WQ Output cell mass=0
WQ Output cell source sink temp=0
WQ Output nsm pathways=0
WQ Output nsm derived pathways=0
WQ Create Restart=0
WQ Fixed Restart=0
WQ System Summary=0
WQ Write To DSS=0
Sorting and Armoring Iterations= 10
XS Update Threshold= 0.02
Bed Roughness Predictor= 0
Hydraulics Update Threshold= 0.02
Energy Slope Method= 1
Volume Change Method= 1
Sediment Retention Method= 0
Sediment TS Multiplier= 1
Warm Up Method= 0
XS Weighting Method= 0
Number of US Weighted Cross Sections= 1
Number of DS Weighted Cross Sections= 1
Upstream XS Weight=0
Main XS Weight=1
Downstream XS Weight=0
Number of DS XS's Weighted with US Boundary= 1
Upstream Boundary Weight= 1
Weight of XSs Associated with US Boundary= 0
Number of US XS's Weighted with DS Boundary= 1
Downstream Boundary Weight= 0.5
Weight of XSs Associated with DS Boundary= 0.5
Percentile Method= 0
Sediment Output Level= 3
Mass or Volume Output= 0
Output Increment Type= 1
Profile and TS Output Increment= 1
Transport Output Increment 1
XS Output Flag= 0
XS Output Increment= 10
Read HDF5 Sediment Hotstart= 0
Sediment Hotstart Type= 0
Write Gradation File= 0
Read Gradation Hotstart= 0
Write HDF5 File= 1
Write Binary Output= 1
Write DSS Sediment File= 0
DSS Sediment Output Type= 1
SV Curve= 0
Specific Gage Flag= 0
Subcell Erosion Methods= 0
Subcell Deposition Methods= 0
Advection Scheme= 1
Matrix Solver= 0
Implicit Weighting Factor= 1
Maximum Outer Loop Convergence Iterations= 5
Convergence Maximum Absolute= 0.001
Convergence RMSE= 0.0001
Grain Fractions Max Abs Error= 0.001
Max Subgrid Regions= 1
Max Subgrid Length Scale= 3.402823E+38
Initial Layer Thickness= 3.402823E+38
Min Layer Thickness= 3.402823E+38
Max Layer Thickness= 3.402823E+38
Number of Layers= 5

--- RFMIDFT1.f01 (steady flow) ---

Flow Title=Flow
Program Version=6.30
Number of Profiles= 1
Profile Names=01Pct
River Rch & RM=River 1,Reach 1         ,896
     348
Boundary for River Rch & Prof#=River 1,Reach 1         , 1
Up Type= 0
Dn Type= 3
Dn Slope=0.01172
DSS Import GetInterval= 0
DSS Import GetPeak= 0
DSS Import FillOption= 0

--- RFMIDFT1.g01 (geometry) ---

Geom Title=Geometry
Program Version=6.30

River Reach=River 1         ,Reach 1
Reach XY= 30
 2211692.4781006670738.7366679162211710.96428409670716.101214498
2211750.88415176670700.0474408422211773.29060301670685.424438596
 2211800.3046566670660.6137926732211813.69701825670641.870063752
2211823.68420301670593.1651086662211833.15629692 670584.66610992
2211903.26639292670576.3672420082211949.99694251670566.408928588
2211999.90399492670579.5437448322212025.71595117670580.287837833
2212032.52663308670595.1109709292212054.18931942670612.395385176
2212069.04099576670618.9770649222212083.89300017670616.287109673
2212100.63345225670626.2457511722212118.51891518670655.520298928
2212124.61404733670679.0999761672212099.11705109670722.081845582
2212096.45563909670732.7271655052212097.60032184670745.289804429
  2212101.778135670751.3563933372212159.21141909670766.208397761
2212237.19092192670771.1591752622212245.94746609670787.126991093
2212249.72501759670811.8516791762212269.31926336670819.630488533
2212299.65610295670814.1576235632212305.68147068670818.322811943

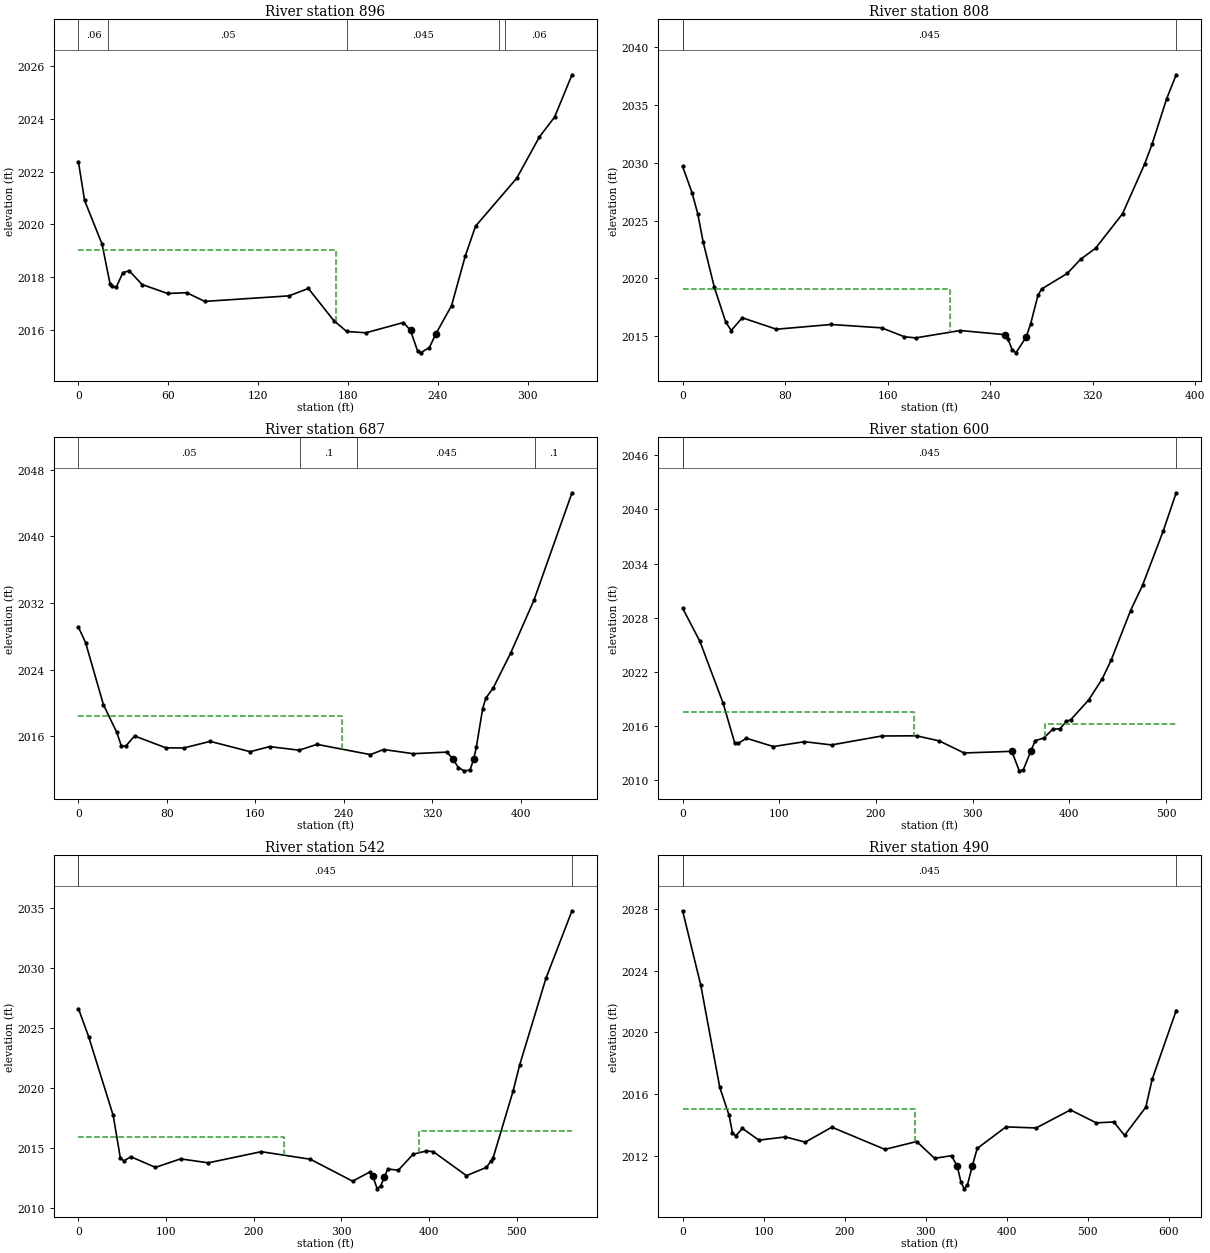
Type RM Length L Ch R = 1 ,896     ,88.2,88.2,88.2
XS GIS Cut Line= 5
2211788.76155608670940.9754173592211719.10417518670754.030834323
2211692.48831042670737.6445390492211661.89962269670722.061622659
  2211610.948738670682.620612235
#Sta/Elev= 30
       0 2022.38     4.1 2020.91    15.8 2019.25    21.1 2017.75    22.1 2017.65
    25.2 2017.61    29.7 2018.17    33.9 2018.24    42.5 2017.72    59.5 2017.38
    72.3 2017.41    84.3 2017.08   140.6 2017.29   153.5 2017.57   170.5 2016.35
   179.1 2015.94   191.9 2015.89     217 2016.28   221.7 2015.98   226.4  2015.2
   228.4 2015.13   234.3 2015.33   238.52015.837   249.1 2016.92   258.2 2018.79
   265.1 2019.93   292.6 2021.75   307.7 2023.31   317.9 2024.07   329.5 2025.67
#Mann= 5 ,-1,0
       0     .06       0      20     .05       0179.0055    .045       0
281.0787     .05       0  285.09     .06       0
#XS Ineff= 2 , 0
          171.94 2019.02
Permanent Ineff=
       T       F
Bank Sta=221.7,238.5
XS Rating Curve= 0 ,0
Exp/Cntr(USF)=0,0
Exp/Cntr=0.3,0.1

Type RM Length L Ch R = 1 ,808     ,124.1,121.1,118.1
XS GIS Cut Line= 3
2211873.67467662670927.9610112312211781.17051431670714.921122293
 2211693.3382794670589.713468267
#Sta/Elev= 30
       0 2029.68     7.4 2027.39    11.8  2025.6    16.1 2023.12    24.8 2019.22
    33.6 2016.25    37.9  2015.5    46.6  2016.6    73.2 2015.61   115.8 2016.02
   155.3 2015.73   173.1 2014.96   181.8 2014.86   216.7  2015.5   251.5 2015.14
   253.9 2014.75   257.2 2013.85   260.1 2013.57     268 2014.91   271.6 2016.07
   277.3 2018.53   280.2 2019.09   300.3 2020.44   310.6 2021.66   322.3 2022.61
   343.3 2025.59   360.6 2029.89   366.3 2031.58   377.8 2035.54   385.2  2037.6
#Mann= 3 ,-1,0
       0     .06       0       0    .045       0 385.199     .05       0
#XS Ineff= 2 , 0
           208.9 2019.08
Permanent Ineff=
       T       F
Bank Sta=251.5,268
XS Rating Curve= 0 ,0
Exp/Cntr(USF)=0,0
Exp/Cntr=0.3,0.1

Type RM Length L Ch R = 1 ,687     ,76.1,86.4,94.1
XS GIS Cut Line= 3
2211892.43090598670923.6641262062211859.32618913670622.656423021
2211749.93076679670529.556029346
#Sta/Elev= 30
       0  2029.1     6.5 2027.24    22.6  2019.8    34.7 2016.46    38.7 2014.88
    42.7 2014.79    50.8 2016.03      79 2014.61    95.1 2014.58   119.2 2015.38
   155.4 2014.14   172.9 2014.75   199.7 2014.32   215.8 2015.02   264.1 2013.79
   276.1  2014.4   302.8  2013.9   333.2 2014.09   338.5 2013.32   343.7 2012.23
     349 2011.84   354.2 2011.93   357.62013.253     360 2014.72   365.7 2019.32
   368.5 2020.56   375.2 2021.79     391 2025.98     412 2032.31   446.5 2045.24
#Mann= 4 ,-1,0
       0     .05       0     200      .1       0252.3239    .045       0
 413.459      .1       0
#XS Ineff= 2 , 0
        238.8851 2018.39
Permanent Ineff=
       T       F
Bank Sta=338.5,357.6
XS Rating Curve= 0 ,0
Exp/Cntr(USF)=0,0
Exp/Cntr=0.3,0.1

Type RM Length L Ch R = 1 ,600     ,54.6,58.4,61.3
XS GIS Cut Line= 4
2211918.52517955670923.1022067462211924.41180806 670646.43066677
2211901.70624095670557.2902921882211829.38480497670435.352987335
#Sta/Elev= 30
       0 2029.07    17.9 2025.39    41.9 2018.55    53.9 2014.13    57.5 2014.08
    65.9 2014.66    93.9 2013.74     126 2014.28     154 2013.92     206 2014.91
     242 2014.93   265.6 2014.36   291.1 2013.03   340.5 2013.21   348.2 2011.05
   352.3 2011.15   360.2 2013.25   364.7  2014.4   373.5 2014.67   382.8 2015.66
   390.4 2015.71   396.8 2016.53   401.4 2016.71     420  2018.9     434 2021.24
   443.3 2023.33   463.3  2028.8   475.8 2031.63   497.2 2037.65   510.5 2041.85
#Mann= 3 ,-1,0
       0     .05       0       0    .045       0510.4921      .1       0
#XS Ineff= 2 ,-1
       0  239.66 2017.56  375.21510.4921 2016.29
Permanent Ineff=
       F       F
Bank Sta=340.5,360.2
XS Rating Curve= 0 ,0
Exp/Cntr(USF)=0,0
Exp/Cntr=0.3,0.1

Type RM Length L Ch R = 1 ,542     ,50.7,51.9,52.2
XS GIS Cut Line= 4
2211933.13747341670912.7366948872211963.17693869670581.689526415
2211962.56388838670544.2934573842211860.79753659670379.995973772
#Sta/Elev= 30
       0  2026.6    11.6 2024.27    39.7 2017.68    47.8 2014.15    51.8 2013.89
    59.8 2014.24    87.9 2013.35   116.5 2014.06   148.2 2013.73   208.6 2014.66
   264.6 2014.03   312.8  2012.2   332.9 2012.98   335.9  2012.6   340.9 2011.56
   344.9 2011.82   348.9 2012.51   352.9 2013.22   364.9 2013.11   381.9 2014.45
     397 2014.72   404.7 2014.67   442.7 2012.66   465.5 2013.35     471 2013.91
   473.1 2014.14   495.9 2019.72   503.5 2021.92   533.4 2029.13   563.1 2034.76
#Mann= 3 ,-1,0
       0     .05       0       0    .045       0  563.07      .1       0
#XS Ineff= 2 ,-1
       0  234.93 2015.87  388.73  563.07 2016.38
Permanent Ineff=
       F       F
Bank Sta=335.9,348.9
XS Rating Curve= 0 ,0
Exp/Cntr(USF)=0,0
Exp/Cntr=0.3,0.1

Type RM Length L Ch R = 1 ,490     ,52.1,59.7,63.8
XS GIS Cut Line= 4
2211941.72017777670921.3193992552212012.83401396670591.498331407
2212017.12536615670522.8366964652211893.28920313670361.604464413
#Sta/Elev= 30
       0 2027.88    22.4 2023.06    45.9 2016.42    57.4 2014.61    61.5 2013.49
    65.6 2013.27    73.8 2013.76    94.3    2013     127 2013.21   151.5 2012.87
   184.3 2013.84   249.8  2012.4   289.1 2012.91   311.1 2011.82   332.1 2011.99
     339 2011.32   343.7 2010.29   347.7 2009.84   351.7 2010.09   357.7 2011.32
   363.8 2012.46   399.3 2013.86   436.6 2013.79   478.9 2014.96   510.8 2014.12
   532.5 2014.18   545.7 2013.31   571.9 2015.13   579.8 2016.94   609.5 2021.41
#Mann= 3 ,-1,0
       0     .05       0       0    .045       0609.4969      .1       0
#XS Ineff= 2 , 0
           287.1 2014.99
Permanent Ineff=
       F       F
Bank Sta=339,357.7
XS Rating Curve= 0 ,0
Exp/Cntr(USF)=0,0
Exp/Cntr=0.3,0.1

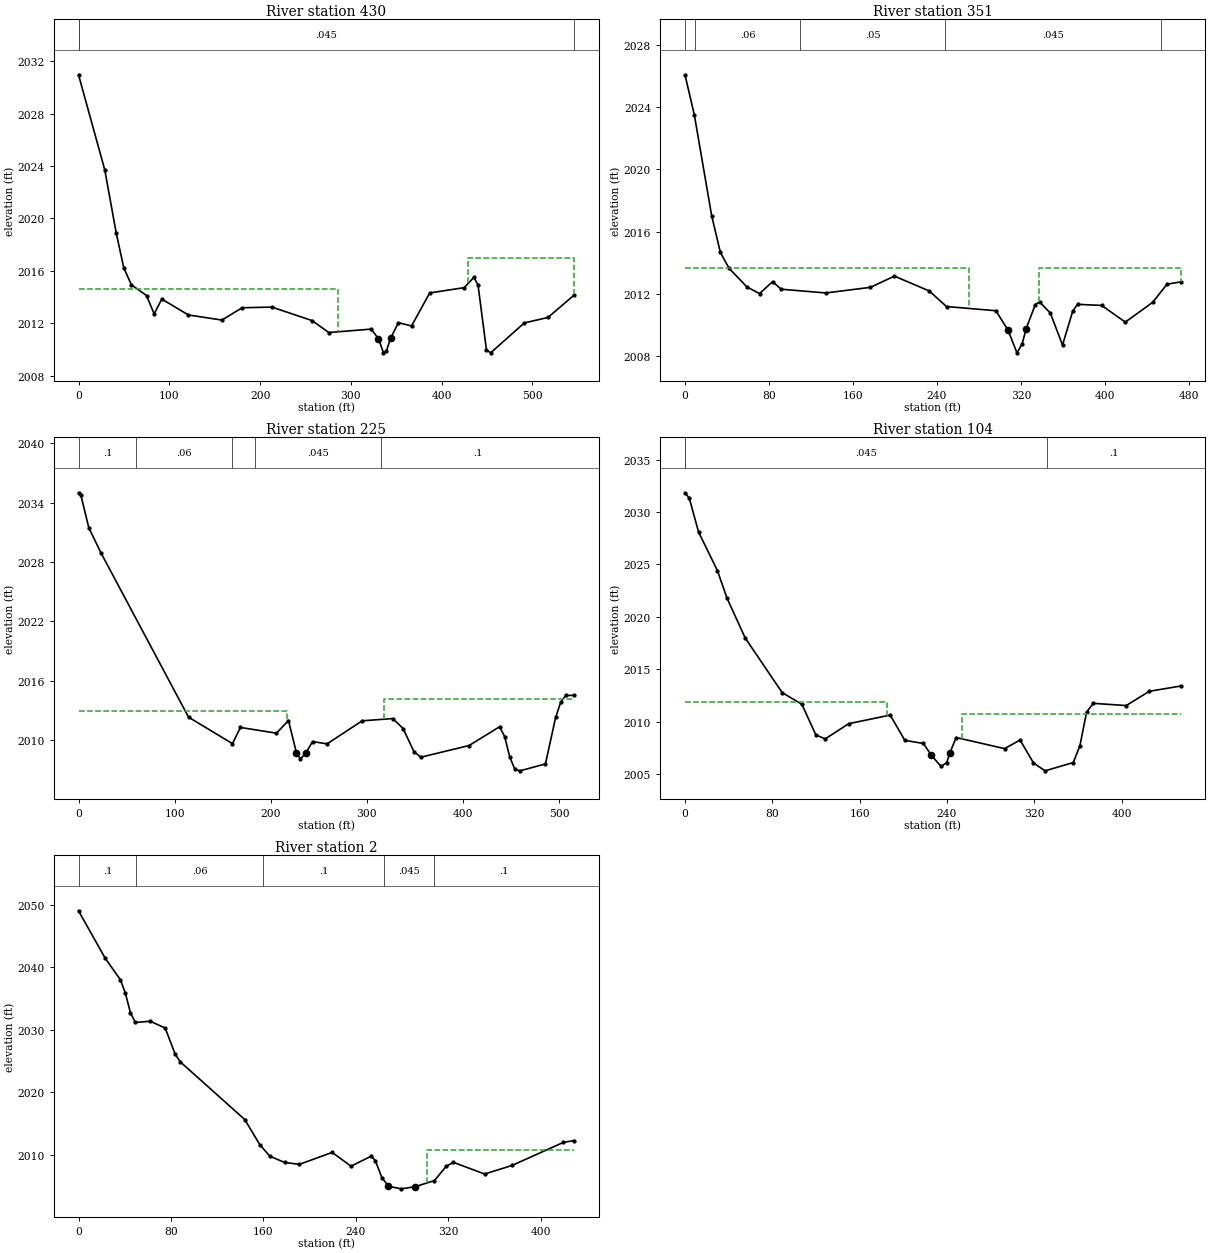
Type RM Length L Ch R = 1 ,430     ,69.3,79.6,86
XS GIS Cut Line= 4
2211954.60497976 670936.842158322212042.43721467670649.985816636
2212082.61579022670547.2034140782212199.52484382670478.605204495
#Sta/Elev= 30
       0 2030.96    28.9 2023.71    41.5  2018.9    49.8 2016.25    58.2 2014.94
    74.9 2014.12    83.3 2012.72    91.7 2013.85     121 2012.64   157.9 2012.25
   180.3 2013.19     213 2013.24   257.2 2012.21   275.7  2011.3   322.3 2011.56
   330.42010.828   335.9 2009.75     339 2009.86   343.8 2010.89   352.4 2012.05
   366.8  2011.8   386.8 2014.32   424.7 2014.72   435.4  2015.5     440 2014.94
   449.3 2009.97   453.9 2009.75     491 2012.03   517.1 2012.45   545.9 2014.16
#Mann= 3 ,-1,0
       0      .1       0       0    .045       0545.9069     .05       0
#XS Ineff= 2 , 0
          285.97 2014.65   429.3         2016.95
Permanent Ineff=
       F       F
Bank Sta=330.4,343.8
XS Rating Curve= 0 ,0
Exp/Cntr(USF)=0,0
Exp/Cntr=0.3,0.1

Type RM Length L Ch R = 1 ,351     ,127.2,125.4,119.5
XS GIS Cut Line= 4
2211988.22081887670925.7343235772212050.04678246670696.977170864
2212166.47623857670619.4786145132212222.90653891670542.656636214
#Sta/Elev= 30
       0 2026.06     8.9 2023.49    25.4 2017.03    33.7 2014.67      42 2013.65
    59.1 2012.45      71 2012.03    83.4 2012.79    91.7 2012.31   134.2 2012.07
   176.6 2012.43   199.5 2013.15   232.6  2012.2   249.1  2011.2   296.1 2010.93
   307.6  2009.7   316.2 2008.23   321.2 2008.81   324.9 2009.77   333.6 2011.31
   337.7  2011.5     348 2010.78   359.6 2008.73   369.3  2010.9   373.9 2011.34
   396.9 2011.27   419.4  2010.2   445.5 2011.47   459.1 2012.63   472.1 2012.78
#Mann= 5 ,-1,0
       0      .1       0      10     .06       0     110     .05       0
247.3999    .045       0453.4209     .05       0
#XS Ineff= 2 , 0
          270.14  2013.7   336.9         2013.64
Permanent Ineff=
       F       F
Bank Sta=307.6,324.9
XS Rating Curve= 0 ,0
Exp/Cntr(USF)=0,0
Exp/Cntr=0.3,0.1

Type RM Length L Ch R = 1 ,225     ,120.4,121.6,123.1
XS GIS Cut Line= 4
2212053.88199194670979.4533982642212100.54113736670812.014029311
2212122.27545293670738.7143196112212322.74759721670564.646319078
#Sta/Elev= 30
       0    2035     2.4 2034.78    10.7 2031.47    23.2 2028.95   114.5  2012.3
   160.2 2009.62   168.5 2011.26     206 2010.68   218.5 2011.96   226.8 2008.69
     231 2008.08   236.52008.647   243.5 2009.83   258.7  2009.6   295.2 2011.93
     327 2012.16   337.8 2011.15   349.1  2008.8   356.3 2008.25   406.4 2009.43
   438.2 2011.33   443.5 2010.33   448.8 2008.26     454 2007.04   459.4 2006.87
   485.9 2007.57   496.5 2012.27   501.8 2013.81   507.1  2014.5   515.8  2014.5
#Mann= 5 ,-1,0
       0      .1       0      60     .06       0     160     .05       0
183.1725    .045       0314.7218      .1       0
#XS Ineff= 2 , 0
          217.01 2012.95  317.75         2014.16
Permanent Ineff=
       F       F
Bank Sta=226.8,236.5
XS Rating Curve= 0 ,0
Exp/Cntr(USF)=0,0
Exp/Cntr=0.3,0.1

Type RM Length L Ch R = 1 ,104     ,95.5,101.5,101.5
XS GIS Cut Line= 4
2212152.31491822  670988.83884692212216.07215066670826.380514224
2212246.72466626670744.2317724192212372.82621487670599.554805515
#Sta/Elev= 30
       0 2031.83     3.9 2031.33    12.5 2028.07    29.7 2024.41    38.3 2021.83
    55.2 2017.97    89.1 2012.76   107.1 2011.65   119.9 2008.73   128.5 2008.35
     150  2009.8     188 2010.62   201.4 2008.21   218.5 2007.91   225.3 2006.84
   234.6 2005.72   239.8 2006.09   242.62006.985   248.4 2008.48   292.8 2007.42
     307 2008.24   319.3 2006.05   329.9  2005.3   355.7 2006.09   361.8 2007.68
   367.9 2010.89     374 2011.74   404.3 2011.53   425.4 2012.89   454.1 2013.39
#Mann= 3 ,-1,0
       0     .06       0       0    .045       0331.8529      .1       0
#XS Ineff= 2 , 0
          185.07 2011.86  253.52         2010.77
Permanent Ineff=
       F       F
Bank Sta=225.3,242.6
XS Rating Curve= 0 ,0
Exp/Cntr(USF)=0,0
Exp/Cntr=0.3,0.1

Type RM Length L Ch R = 1 ,2       ,361.7,,341.8
XS GIS Cut Line= 3
2212183.92322558671066.8862992132212263.51205812670866.383663368
2212398.20085167670701.083780382
#Sta/Elev= 30
       0 2049.02    23.1 2041.43    36.3 2037.97    40.6 2035.81    44.9 2032.72
    49.2 2031.15    62.1 2031.35      75 2030.26    83.6  2026.1    87.9 2024.88
   143.9 2015.62   156.8 2011.63   165.4 2009.78   178.3 2008.76   191.2 2008.46
   219.5 2010.37   235.8 2008.16   253.4 2009.78   256.9 2009.03   262.5 2006.34
   268.2 2004.95   279.2 2004.54     291 2004.87     308 2005.86   318.1 2008.13
   324.4 2008.78   351.4 2006.91   375.1 2008.28   419.4 2011.96   428.9 2012.27
#Mann= 5 ,-1,0
       0      .1       0      50     .06       0     160      .1       0
     264    .045       0   307.9      .1       0
#XS Ineff= 2 , 0
                          301.41          2010.8
Permanent Ineff=
       F       F
Bank Sta=268.2,291
XS Rating Curve= 0 ,0
Exp/Cntr(USF)=0,0
Exp/Cntr=0.3,0.1
LCMann Table=0

Chan Stop Cuts=-1
Use User Specified Reach Order=0
Composite Channel Slope=5